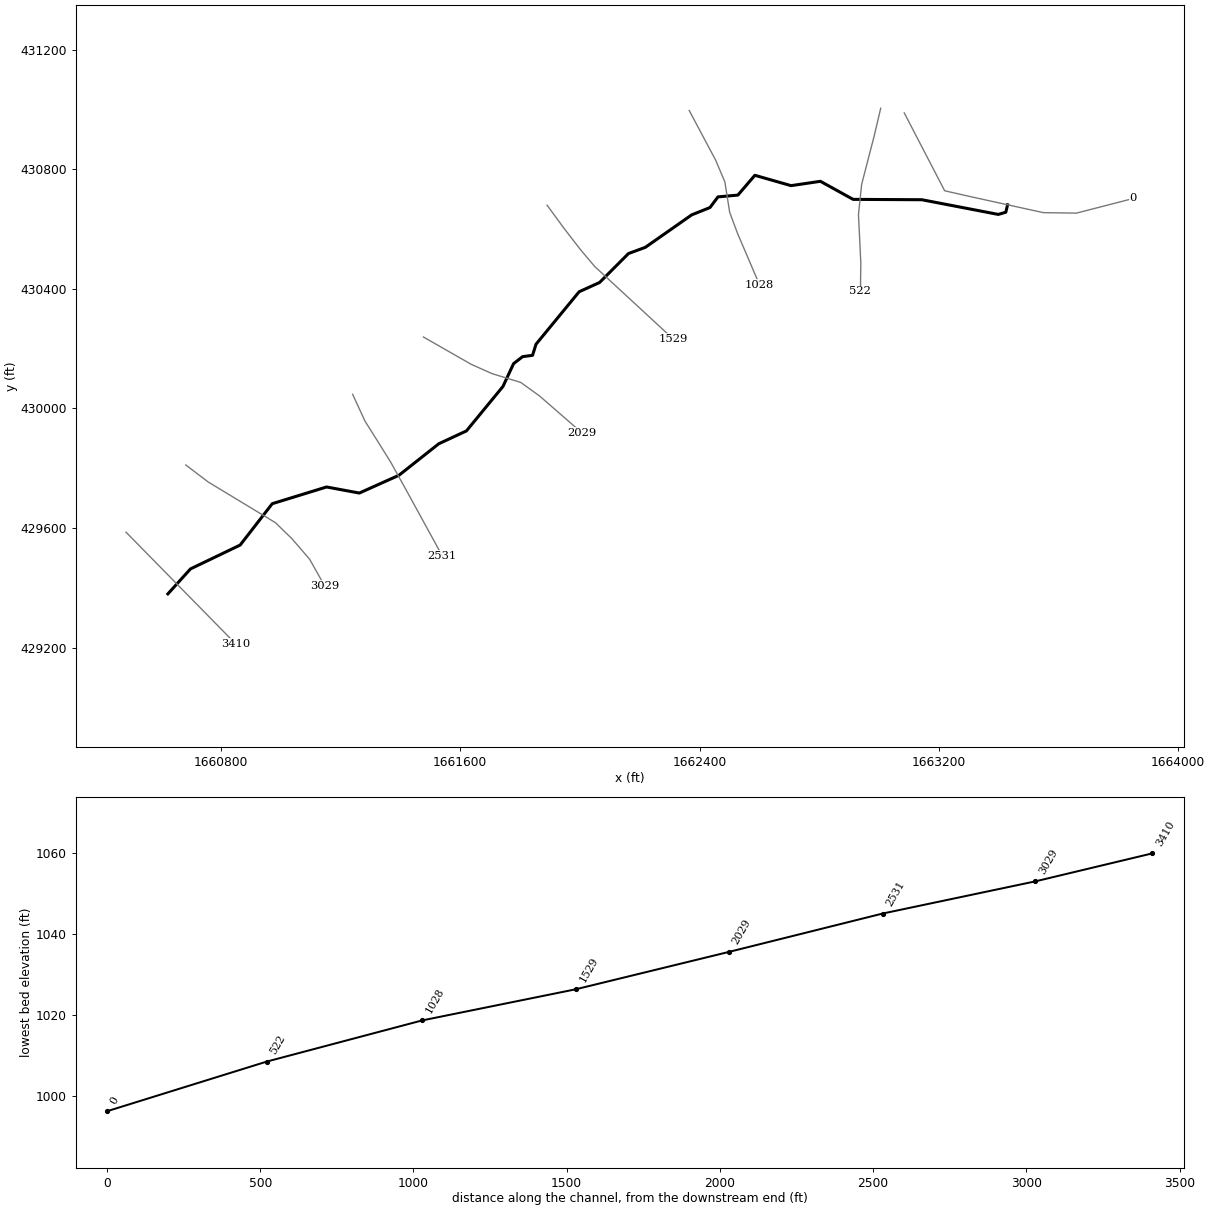
--- MILLERRN.prj (project) ---

Proj Title=MILLERRN
Current Plan=p01
Default Exp/Contr=0,0
English Units
Geom File=g01
Flow File=f01
Plan File=p01
BEGIN DESCRIPTION:
---------- MODELED AS PART OF WVEMD CTP PROGRAM, 2023----------
Stream Name:Miller Run
Flood Zone:  AFH
Wetzel County, WV
HEC-RAS Version: RAS 6.3
Vertical Datum: NAVD88
Projection: NAD 1983 StatePlane West Virginia S FIPS 4702 (US Feet)
Terrain: 1-meter West Virginia FEMA R3 South Central (collected 2018-2020)
Land Use: 2019 NLCD
Hydrologic Method:
WV SIR2010-5033 regression equations
Additional Model Notes:
None
END DESCRIPTION:
DSS Export Rating Curves= 0
DSS Export Rating Curve Sorted= 0
DSS Export Volume Flow Curves= 0
DXF OffsetX= 0
DXF OffsetY= 0
DXF ScaleX= 0
DXF ScaleY= 0

--- MILLERRN.p01 (plan) ---

Plan Title=Floodplain
Program Version=6.30
Short Identifier=Floodplain
Geom File=g01
Flow File=f01
Subcritical Flow
K Sum by GR= 0
Std Step Tol= 0.01
Critical Tol= 0.01
Num of Std Step Trials= 20
Max Error Tol= 0.3
Flow Tol Ratio= 0.001
Split Flow NTrial= 30
Split Flow Tol= 0.02
Split Flow Ratio= 0.02
Log Output Level= 0
Friction Slope Method= 1
Unsteady Friction Slope Method= 2
Unsteady Bridges Friction Slope Method= 1
Parabolic Critical Depth
Global Vel Dist= 0 , 0 , 0
Global Log Level= 0
CheckData=True
Encroach Param=-1 ,0,0, 0
Mapping Interval=1HOUR
Computation Time Step Use Courant=        0
Computation Time Step Use Time Series=    0
Computation Time Step Count To Double=0
Computation Time Step Max Doubling=0
Computation Time Step Max Halving=0
Computation Time Step Residence Courant=0
Run HTab= 0
Run UNet= 0
Run Sediment= 0
Run PostProcess= 0
Run WQNet= 0
Run RASMapper= 0
UNET Theta= 0
UNET Theta Warmup= 0
UNET ZTol= 0
UNET ZSATol= 0
UNET MxIter= 0
UNET Max Iter WO Improvement= 0
UNET MaxInSteps= 0
UNET DtIC= 0
UNET DtMin= 0
UNET MaxCRTS= 0
UNET WFStab= 0
UNET SFStab= 0
UNET WFX= 1
UNET SFX= 1
UNET Gravity=32.17405
UNET 1D Methodology=Finite Difference
UNET DSS MLevel= 1
UNET Pardiso=0
UNET DZMax Abort= 0
UNET Use Existing IB Tables= 0
UNET Froude Reduction=False
UNET Froude Limit= 0
UNET Froude Power= 0
UNET D1 Cores= 0
UNET WindReference=Eulerian
UNET WindDragFormulation=Hsu (1988)
UNET D2 Coriolis=0
UNET D2 Cores= 0
UNET D2 Theta= 1
UNET D2 Theta Warmup= 1
UNET D2 Z Tol= 0.01
UNET D2 Volume Tol= 0.01
UNET D2 Max Iterations= 20
UNET D2 Equation= 0
UNET D2 RampUpFraction=0.1
UNET D2 TimeSlices= 1
UNET D2 Turbulence Formulation=Non-Conservative (original)
UNET D2 Eddy Viscosity=0.3
UNET D2 Transverse Eddy Viscosity=0.1
UNET D2 Smagorinsky Mixing=0
UNET D2 BCVolumeCheck=0
UNET D2 Cores=0
UNET D2 SolverType=PARDISO (Direct)
UNET D2 Minimum Iterations= 3
UNET D2 Maximum Iterations= 30
UNET D2 Restart Number= 10
UNET D2 Relaxation Coeff=1.3
UNET D2 SOR Precondition Iterations= 10
UNET D2 ILUT Maximum Fill= 8
UNET D2 ILUT Tolerance=1E-08
UNET D2 Convergence Tolerance=0.00001
UNET D1D2 MaxIter= 0
UNET D1D2 ZTol=0.01
UNET D1D2 QTol=0.1
UNET D1D2 MinQTol=1
Write IC File= 0
Write IC File at Fixed DateTime=0
Write IC File at Sim End=0
Echo Input=False
Echo Parameters=False
Echo Output=False
Write Detailed= 0
HDF Write Warmup=0
HDF Write Time Slices=0
HDF Flush=0
HDF Compression= 1
HDF Chunk Size= 1
HDF Spatial Parts= 1
HDF Use Max Rows=0
HDF Fixed Rows= 1
Calibration Method= 0
Calibration Iterations= 20
Calibration Max Change=0.05
Calibration Tolerance=0.2
Calibration Maximum=1.5
Calibration Minimum=0.5
Calibration Optimization Method= 1
WQ AD Non Conservative
WQ ULTIMATE=-1
WQ Max Comp Step=1HOUR
WQ Output Interval=15MIN
WQ Output Selected Increments= 0
WQ Output face flow=0
WQ Output face velocity=0
WQ Output face area=0
WQ Output face dispersion=0
WQ Output cell volume=0
WQ Output cell surface area=0
WQ Output cell continuity=0
WQ Output cumulative cell continuity=0
WQ Output face conc=0
WQ Output face dconc_dx=0
WQ Output face courant=0
WQ Output face peclet=0
WQ Output face adv mass=0
WQ Output face disp mass=0
WQ Output cell mass=0
WQ Output cell source sink temp=0
WQ Output nsm pathways=0
WQ Output nsm derived pathways=0
WQ Create Restart=0
WQ Fixed Restart=0
WQ System Summary=0
WQ Write To DSS=0
Sorting and Armoring Iterations= 10
XS Update Threshold= 0.02
Bed Roughness Predictor= 0
Hydraulics Update Threshold= 0.02
Energy Slope Method= 1
Volume Change Method= 1
Sediment Retention Method= 0
Sediment TS Multiplier= 1
Warm Up Method= 0
XS Weighting Method= 0
Number of US Weighted Cross Sections= 1
Number of DS Weighted Cross Sections= 1
Upstream XS Weight=0
Main XS Weight=1
Downstream XS Weight=0
Number of DS XS's Weighted with US Boundary= 1
Upstream Boundary Weight= 1
Weight of XSs Associated with US Boundary= 0
Number of US XS's Weighted with DS Boundary= 1
Downstream Boundary Weight= 0.5
Weight of XSs Associated with DS Boundary= 0.5
Percentile Method= 0
Sediment Output Level= 3
Mass or Volume Output= 0
Output Increment Type= 1
Profile and TS Output Increment= 1
Transport Output Increment 1
XS Output Flag= 0
XS Output Increment= 10
Read HDF5 Sediment Hotstart= 0
Sediment Hotstart Type= 0
Write Gradation File= 0
Read Gradation Hotstart= 0
Write HDF5 File= 1
Write Binary Output= 1
Write DSS Sediment File= 0
DSS Sediment Output Type= 1
SV Curve= 0
Specific Gage Flag= 0
Subcell Erosion Methods= 0
Subcell Deposition Methods= 0
Advection Scheme= 1
Matrix Solver= 0
Implicit Weighting Factor= 1
Maximum Outer Loop Convergence Iterations= 5
Convergence Maximum Absolute= 0.001
Convergence RMSE= 0.0001
Grain Fractions Max Abs Error= 0.001
Max Subgrid Regions= 1
Max Subgrid Length Scale= 3.402823E+38
Initial Layer Thickness= 3.402823E+38
Min Layer Thickness= 3.402823E+38
Max Layer Thickness= 3.402823E+38
Number of Layers= 5

--- MILLERRN.f01 (steady flow) ---

Flow Title=Flow
Program Version=6.30
Number of Profiles= 1
Profile Names=F01pct
River Rch & RM=MILLERRN,Main            ,3410
     624
River Rch & RM=MILLERRN,Main            ,1028
     696
River Rch & RM=MILLERRN,Main            ,0
    2080
Boundary for River Rch & Prof#=MILLERRN,Main            , 1
Up Type= 0
Dn Type= 1
Dn Known WS=1002.6
DSS Import GetInterval= 0
DSS Import GetPeak= 0
DSS Import FillOption= 0

--- MILLERRN.g01 (geometry) ---

Geom Title=Geometry
Program Version=6.31

River Reach=MILLERRN        ,Main
Reach XY= 30
1660622.57644501429379.4524507471660698.26199999429463.075000003
1660864.21100001429542.7910000091660971.50100002429681.165000007
     1661152.992      429737.0661661262.53800002429716.761000007
1661394.89500001429776.1720000211661528.25600001429881.707000017
     1661620.505429924.5729999991661742.58499999430073.224000022
1661778.18099999430149.6809999941661808.26300001430172.994000003
     1661841.603430177.5059999971661853.13400002430214.606999993
     1661997.273      430390.0811662065.70900002430421.165000007
1662162.21900001430517.9270000011662218.62200001430538.732999995
1662373.54100001430647.276000008     1662434.706430671.842999995
     1662461.278430707.4389999961662527.95800002430713.454999998
1662584.61100002430779.6340000031662705.68799999430745.040000007
1662803.70299999430759.580000013     1662912.999430699.165999994
1663142.87000002430697.913000017      1663398.31430648.780000016
1663423.48238693430656.098830789  1663429.378598 430681.01519537

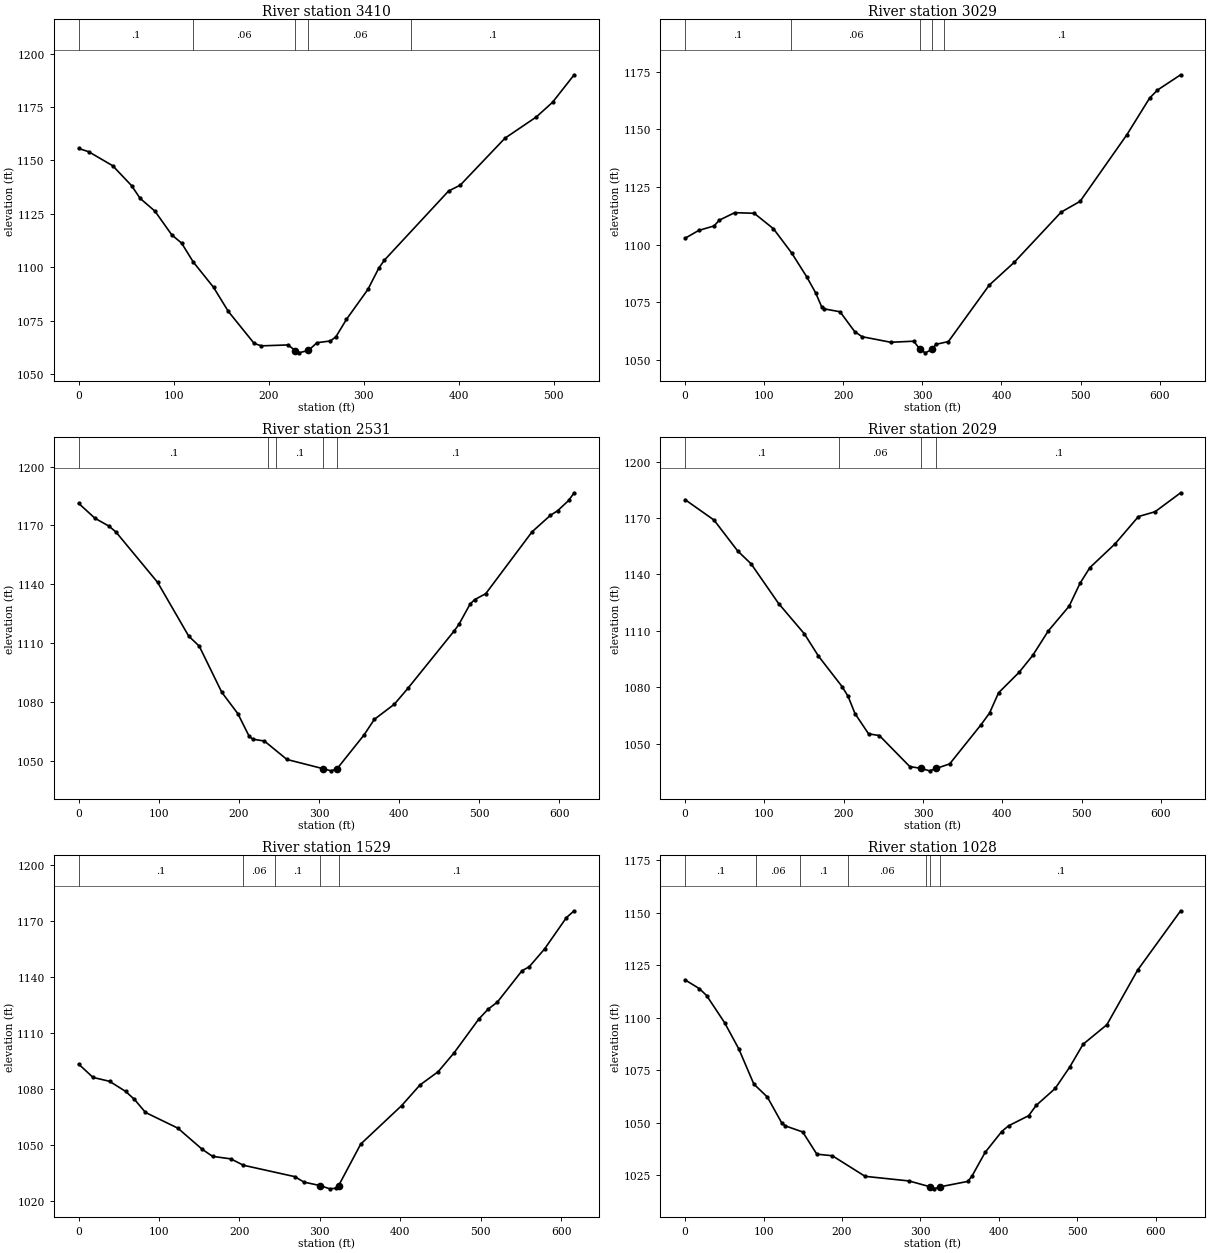
Type RM Length L Ch R = 1 ,3410    ,377,380.8,381.7
XS GIS Cut Line= 2
1660482.71898917429585.8813776341660848.06223906429213.512296008
#Sta/Elev= 30
       0 1155.57    10.4  1154.1    35.9 1147.49    55.7  1138.2    64.8 1132.19
    80.3 1126.26    98.1 1115.12   108.4 1111.29   120.7 1102.42     142  1090.6
   157.5 1079.36   184.8 1064.31   192.4 1063.18   220.4 1063.61   228.2 1060.97
   231.6 1059.91   241.9 1061.02   250.9 1064.65     265 1065.46   270.9 1067.44
     282 1075.61   304.5 1089.57   315.9 1099.48   321.8 1103.24   389.4 1135.63
   401.8 1138.43   448.8 1160.38   481.8 1170.32   498.9 1177.19   521.7 1190.08
#Mann= 5 ,-1,0
       0      .1       0     120     .06       0   228.2    .045       0
   241.9     .06       0     350      .1       0
Bank Sta=228.2,241.9
XS Rating Curve= 0 ,0
Exp/Cntr(USF)=0,0
Exp/Cntr=0.3,0.1

Type RM Length L Ch R = 1 ,3029    ,503.6,498.6,496.2
XS GIS Cut Line= 6
1660682.48591758429810.7039967631660757.48806417429753.713297084
1660982.04273318429617.7631096691661037.37825242429563.989267096
1661096.36074601429495.4887479251661146.46366417429406.355396003
#Sta/Elev= 30
       0 1102.76    17.1 1106.13    36.6 1108.11    43.3 1110.61    62.7 1113.87
    87.4 1113.59   111.7 1106.89   134.9 1096.29   153.7 1086.04     165  1079.1
   172.5  1073.1   175.5 1072.12   195.9 1070.84   214.5 1062.18   223.8 1060.02
     260  1057.6   289.1 1058.06   296.9 1054.56   303.7 1053.01   312.4 1054.52
   317.1 1056.69   332.9 1057.91   384.5  1082.4   415.9 1092.24   475.4 1114.09
   499.4 1118.79   558.6 1147.74   587.3 1163.61   597.2 1167.09   626.5 1173.73
#Mann= 5 ,-1,0
       0      .1       0   134.2     .06       0   296.9    .045       0
   312.4     .06       0   326.7      .1       0
Bank Sta=296.9,312.4
XS Rating Curve= 0 ,0
Exp/Cntr(USF)=0,0
Exp/Cntr=0.3,0.1

Type RM Length L Ch R = 1 ,2531    ,491.2,501.6,505.9
XS GIS Cut Line= 6
1661240.25612751430046.9702565071661281.43419476429957.494713679
1661328.45575425429882.7196007521661368.23028101429818.667235419
1661416.81023633429731.2130140071661539.86346792429506.489054009
#Sta/Elev= 30
       0 1181.27    20.3 1173.69    37.9 1169.65    46.7 1166.61    98.5 1141.06
   137.4 1113.64   150.5 1108.57   178.7 1085.03   198.8 1074.12   212.9 1062.58
   217.6 1061.14   231.8 1060.24     260 1050.84  305.171046.139     315 1045.05
   322.5  1046.1   356.2 1063.31   369.1 1071.26   394.1    1079   410.9 1087.03
   469.1 1116.48   474.8 1119.74   488.4 1129.84   494.1  1132.2   508.1 1135.24
     566 1166.79   588.8 1175.14   597.9 1177.51   611.6 1182.73   618.5 1186.64
#Mann= 5 ,-1,0
       0      .1       0  236.83     .06       0  246.83      .1       0
  305.17    .045       0   322.5      .1       0
Bank Sta=305.17,322.5
XS Rating Curve= 0 ,0
Exp/Cntr(USF)=0,0
Exp/Cntr=0.3,0.1

Type RM Length L Ch R = 1 ,2029    ,501.4,499.9,493.9
XS GIS Cut Line= 6
1661476.86490625430238.7464477571661636.61688334 430147.33915025
1661706.09673126430116.2765483411661801.89443992 430086.88782759
 1661864.6249575430041.781618595  1662005.725069429919.037441507
#Sta/Elev= 30
       0 1179.75    36.5 1168.88    66.2 1152.51    83.2 1145.62   117.9 1124.52
   150.4 1108.39   168.1 1096.58     198 1080.31   205.5 1075.14   214.2 1066.01
   231.3 1055.24   244.9 1054.34   283.2 1037.86  297.431036.862   308.3 1035.57
   316.7 1036.88   333.5 1039.24     373 1060.05   383.8  1066.3   395.2 1077.08
     421 1087.92   438.2 1096.92   457.9 1109.99   484.1 1123.09   497.8 1135.23
   510.2 1143.57     542 1156.24   571.5 1170.76   592.5 1173.33   624.7  1183.4
#Mann= 4 ,-1,0
       0      .1       0  194.11     .06       0  297.43    .045       0
   316.7      .1       0
Bank Sta=297.43,316.7
XS Rating Curve= 0 ,0
Exp/Cntr(USF)=0,0
Exp/Cntr=0.3,0.1

Type RM Length L Ch R = 1 ,1529    ,505,501.5,494.4
XS GIS Cut Line= 6
1661890.13278051430679.5867734251661946.49651292430602.640404999
1662000.78249359430532.1845091731662049.58751409 430474.40411292
1662242.33089501430296.2017134281662311.16901192430232.559124172
#Sta/Elev= 30
       0 1093.15    17.9 1086.01    38.5 1083.92    58.3 1078.55    69.4 1074.26
    83.1 1067.25   123.3 1058.86   153.6 1047.54   166.5 1043.73   189.3 1042.38
   204.8 1038.98   268.8 1032.86   280.1 1029.96  300.541028.034   312.4 1026.33
   319.7 1026.66   323.3 1028.06   350.8 1050.32   401.8 1070.97   424.4 1081.94
   447.1  1089.1   466.9  1099.2   497.6 1117.27   509.3 1122.62   520.7 1126.37
   551.4  1143.2   560.3 1145.27   579.4 1154.84   606.6 1171.64   616.2 1175.28
#Mann= 5 ,-1,0
       0      .1       0  204.33     .06       0  244.33      .1       0
  300.54    .045       0   323.3      .1       0
Bank Sta=300.54,323.3
XS Rating Curve= 0 ,0
Exp/Cntr(USF)=0,0
Exp/Cntr=0.3,0.1

Type RM Length L Ch R = 1 ,1028    ,505.2,506.4,501.5
XS GIS Cut Line= 6
 1662365.1436415430996.5841709231662453.27568309 430830.88633959
1662484.35632959430757.7726406751662500.53247835430655.655718923
1662527.44909118430583.664393082 1662599.8872665430414.339272425
#Sta/Elev= 30
       0 1118.05    18.3 1113.86    27.4 1110.62    50.3 1097.73    68.5 1085.17
    87.6 1068.49   104.9 1062.28   122.9 1050.17   127.4 1048.63   149.9 1045.69
   167.9 1035.13   187.7 1034.37   229.4 1024.58   285.5 1022.38  312.231019.605
     317 1018.63   325.1 1019.59   360.4 1022.18   365.6 1024.67   382.4 1035.97
   403.6 1045.91   412.3 1048.63   437.9 1053.44   447.4 1058.31   471.7 1066.39
   490.4 1076.68   507.2 1087.41   537.6 1096.73   576.8 1122.73   631.6 1150.94
#Mann= 7 ,-1,0
       0      .1       0      90     .06       0   146.5      .1       0
   207.7     .06       0  307.14      .1       0  312.23    .045       0
   325.1      .1       0
Bank Sta=312.23,325.1
XS Rating Curve= 0 ,0
Exp/Cntr(USF)=0,0
Exp/Cntr=0.3,0.1

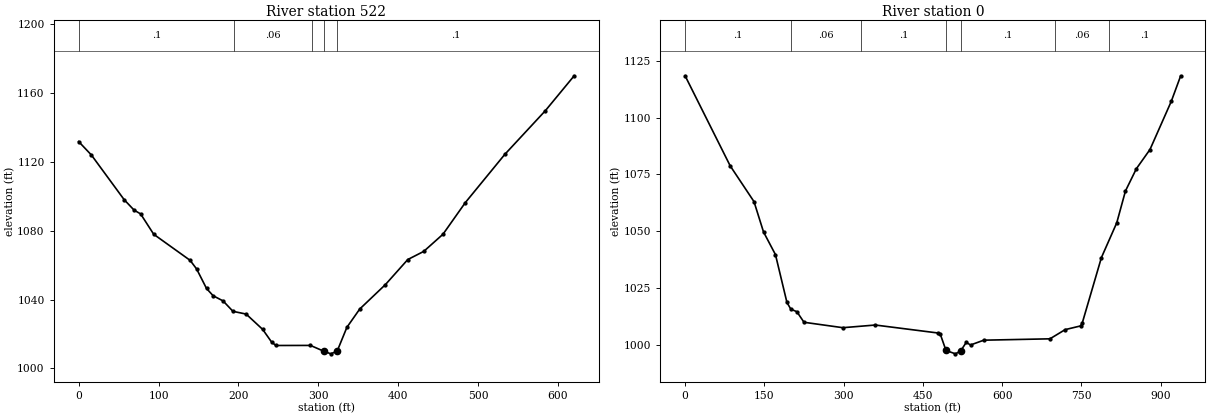
Type RM Length L Ch R = 1 ,522     ,497.6,521.6,538
XS GIS Cut Line= 6
1663005.35036634431004.0684079231662983.53315276430911.315312594
1662941.60836785430749.3248229181662930.97453085430648.527452335
1662938.83606367430486.2174095061662937.54144683430392.364250749
#Sta/Elev= 30
       0 1131.81      16 1123.98      57 1098.03    69.4 1091.98    77.6 1089.76
      94 1077.93   139.5 1062.81   147.7 1057.78   160.1 1046.44   168.4 1042.21
   180.8 1039.22   193.2 1033.16   209.7 1031.57   230.4 1022.66   241.5 1015.34
   246.9 1013.32   290.2 1013.36   306.8 1010.01   315.7 1008.47   323.7 1010.12
   335.8 1023.87   351.9 1034.52     384 1048.69     412 1063.25     432 1067.99
   456.1 1077.97   484.1 1096.37   533.5 1124.37   584.2 1149.72   620.3 1170.02
#Mann= 5 ,-1,0
       0      .1       0  194.77     .06       0  292.61      .1       0
   306.8    .045       0   323.7      .1       0
Bank Sta=306.8,323.7
XS Rating Curve= 0 ,0
Exp/Cntr(USF)=0,0
Exp/Cntr=0.3,0.1

Type RM Length L Ch R = 1 ,0       ,230.9,236.3,241.5
BEGIN DESCRIPTION:
Structure XS 4
END DESCRIPTION:
XS GIS Cut Line= 6
1663084.02974235430988.2860449211663219.11109367430727.906859641
1663304.43441384430708.5020428051663548.59567092430654.787255217
1663659.44366111430653.0637656841663849.21704817430702.061532839
#Sta/Elev= 30
       0 1118.38    85.3 1078.81   130.4 1063.07   148.4 1049.75     171 1039.79
   192.7 1018.78     200 1015.84   211.5  1014.7     225 1010.06   298.5 1007.68
     360 1008.85   478.8 1005.34   482.9 1004.83  493.69997.6691   511.6  996.19
   521.5   997.5     532 1001.21   540.2 1000.09   565.2 1002.19   690.4 1002.79
   719.2 1006.83   748.4 1008.46   751.7 1009.86   787.8  1038.5   816.8 1053.76
   833.3 1067.76   853.9 1077.53   879.7 1085.98     920 1107.15   937.7 1118.31
#Mann= 7 ,-1,0
       0      .1       0     200     .06       0  333.33      .1       0
  493.69    .045       0   521.5      .1       0  700.84     .06       0
   801.7      .1       0
Bank Sta=493.69,521.5
XS Rating Curve= 0 ,0
Exp/Cntr=0.3,0.1
LCMann Table=0

Chan Stop Cuts=-1
Use User Specified Reach Order=0
Composite Channel Slope=5